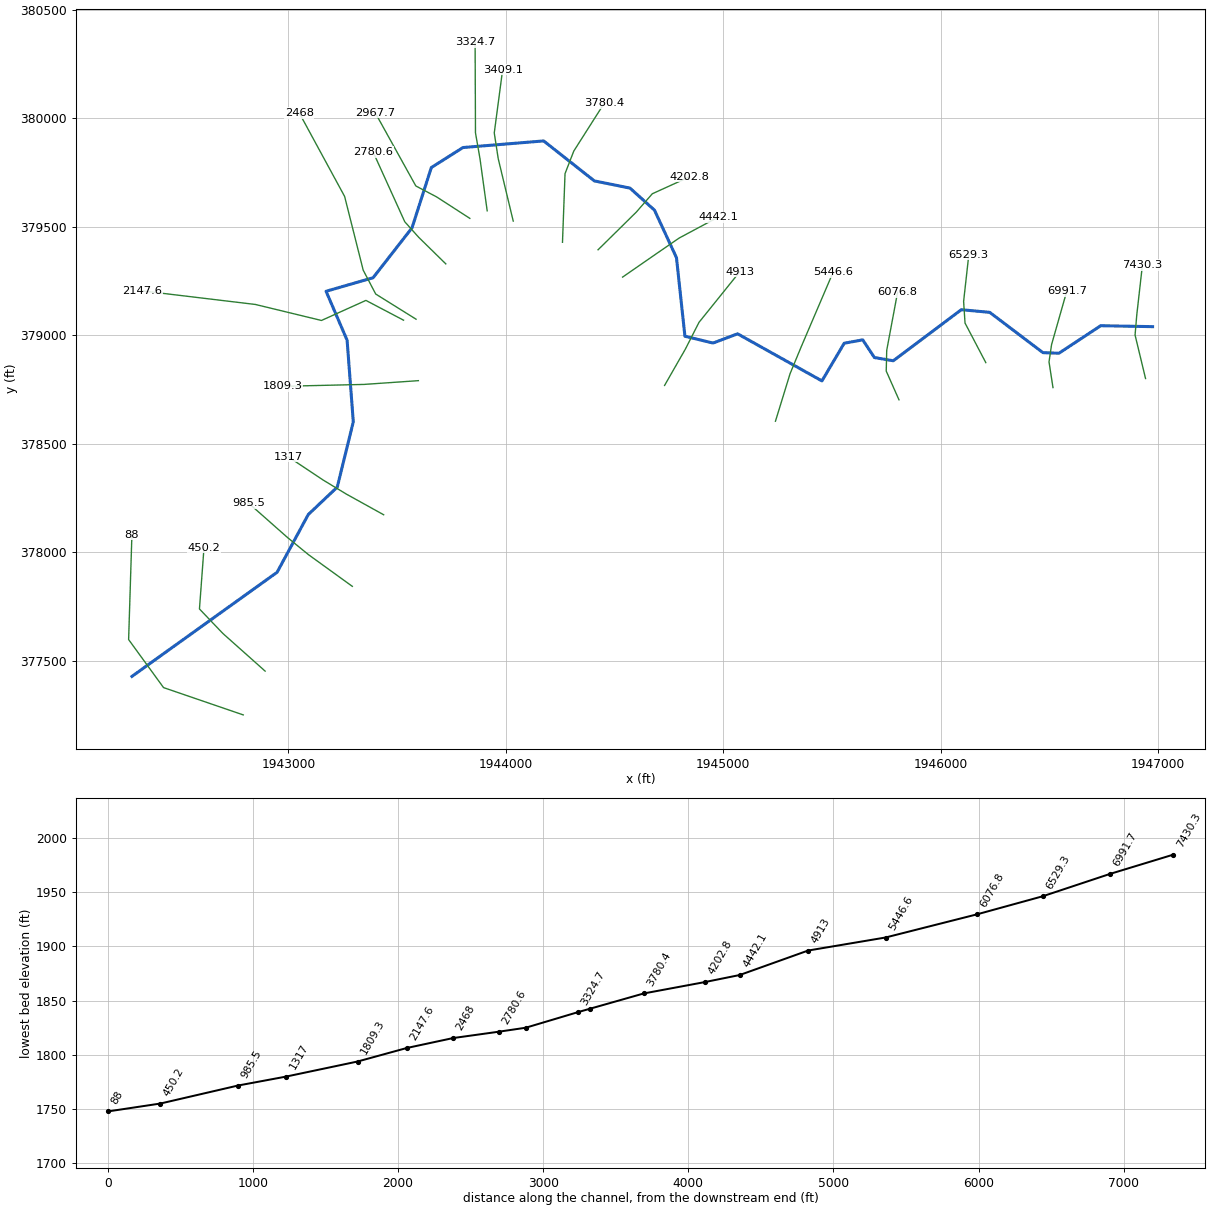
--- LICKRN2.prj (project) ---

Proj Title=LICKRN2
Current Plan=p01
Default Exp/Contr=0,0
English Units
Geom File=g01
Flow File=f01
Plan File=p01
BEGIN DESCRIPTION:
END DESCRIPTION:
DSS Export Rating Curves= 0
DSS Export Rating Curve Sorted= 0
DSS Export Volume Flow Curves= 0
DXF OffsetX= 0
DXF OffsetY= 0
DXF ScaleX= 0
DXF ScaleY= 0

--- LICKRN2.p01 (plan) ---

Plan Title=Floodplain
Program Version=4.00
Geom File=g01
Flow File=f01
K Sum by GR=0
Std Step Tol=0.01
Critical Tol=0.01
Num of Std Step Trials=20
Max Error Tol=0.3
Flow Tol Ratio=0.001
Split Flow NTrial=30
Split Flow Tol=0.02
Split Flow Ratio=0.02
Log Output Level=0
Friction Slope Method=1
Unsteady Friction Slope Method=2
Unsteady Bridges Friction Slope Method=1
Global Log Level=0
CheckData=False
Run HTab=0
Run UNet=0
Run PostProcess=0
UNET Theta=0
UNET Theta Warmup=0
UNET ZTol=0
UNET ZSATol=0
UNET MxIter=0
UNET MaxInSteps=0
UNET DtIC=0
UNET DtMin=0
UNET MaxCRTS=0
UNET WFStab=0
UNET SFStab=0
UNET WFX=0
UNET SFX=0
UNET DSS MLevel=0
UNET DZMax Abort=0
UNET Convert EG Bridges=0
UNET Use Existing IB Tables=0
UNET Froude Limit=0
UNET Froude Power=0
Write IC File=0
Echo Input=False
Echo Output=False
Write Detailed=0

--- LICKRN2.f01 (steady flow) ---

Flow Title=NFF Regression Equation
Program Version=4.00
Number of Profiles=1
Profile Names=P100yr
River Rch & RM=LICKRN2,Main      ,7430.3
539.9533
River Rch & RM=LICKRN2,Main      ,4913
597.4497
River Rch & RM=LICKRN2,Main      ,2468
663.3928
River Rch & RM=LICKRN2,Main      ,2147.6
1095.523
River Rch & RM=LICKRN2,Main      ,88
1122.223
Boundary for River Rch & Prof#=LICKRN2,Main      ,1
Up Type=0
Dn Type=3
Dn Slope=0.019589

--- LICKRN2.g01 (geometry) ---

Geom Title=USGS 10m DEM
Program Version=4.10

River Reach=LICKRN2         ,Main
Reach XY= 30
     1946974.891      379038.832     1946736.176      379043.173
     1946544.336      378916.437     1946470.551      378919.041
     1946225.759      379104.805     1946095.139       379116.96
     1945782.183      378881.714     1945695.377      378896.471
     1945641.558      378978.069     1945556.489      378962.444
     1945454.058      378788.832     1945066.037      379005.846
      1944953.19      378963.312      1944823.85      378994.562
     1944785.004      379356.541     1944683.881      379575.587
     1944571.158      379677.301     1944407.046      379710.562
      1944174.11      379894.735     1943802.868      379864.266
     1943657.327      379771.966     1943568.641      379494.345
     1943389.605       379264.31     1943173.335      379201.845
     1943269.981      378976.337     1943298.459      378600.247
     1943224.693      378299.358     1943091.433      378173.149
     1942947.982      377906.888     1942280.379      377427.172

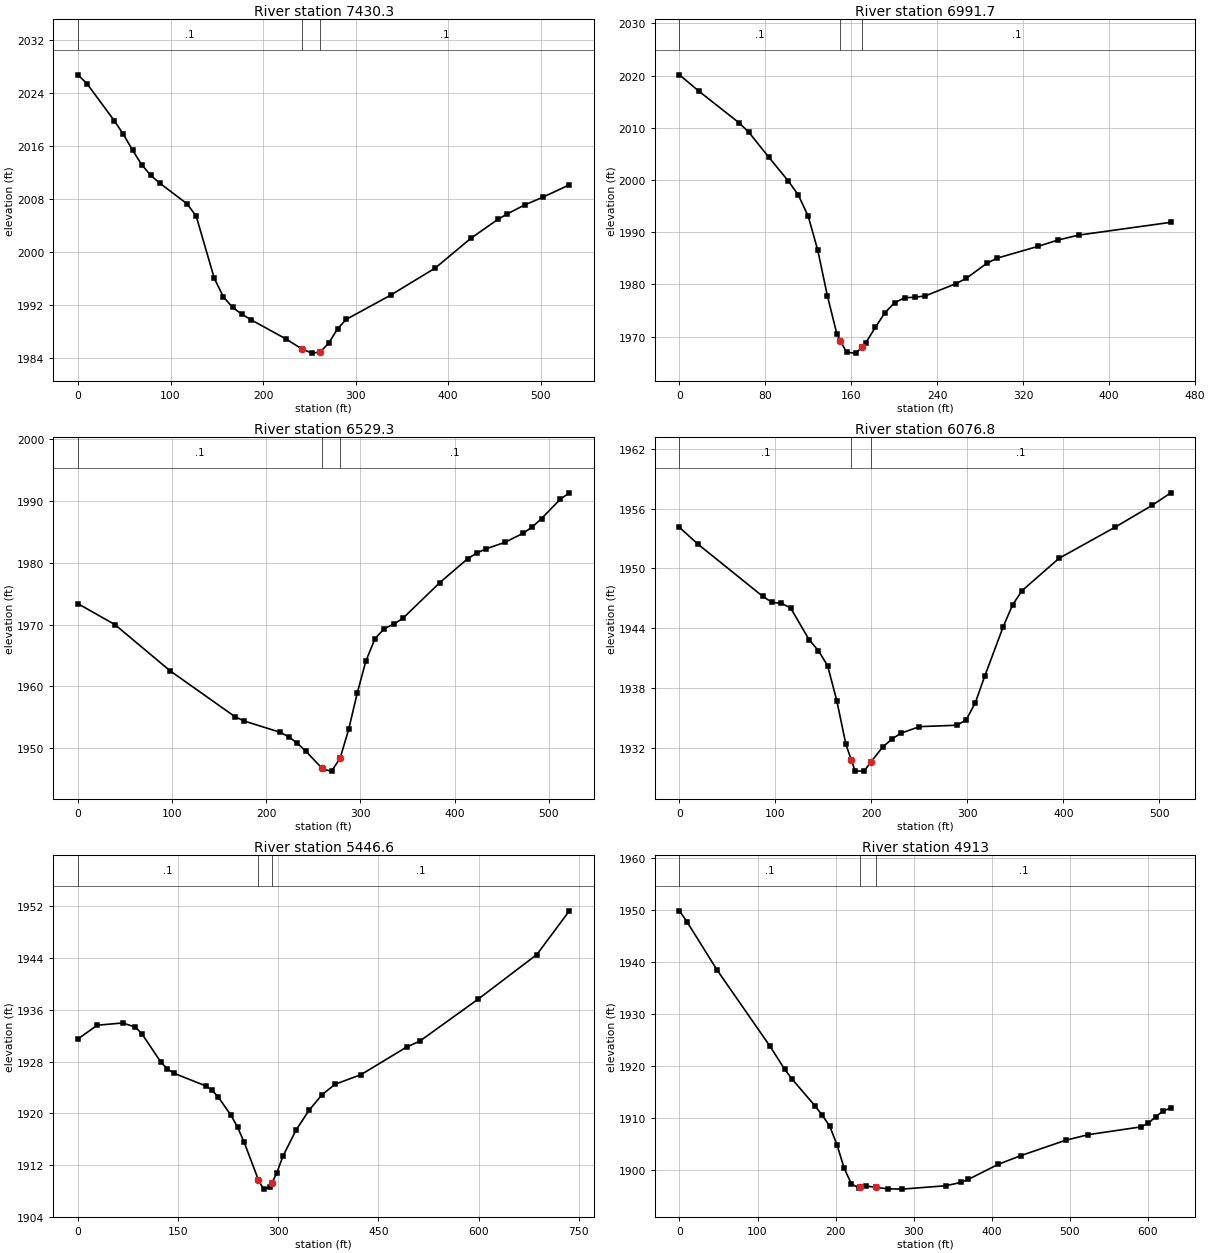
Type RM Length L Ch R = 1 ,7430.3  ,440.3,438.6,436.6
XS GIS Cut Line= 4
     1946942.506      378799.771     1946894.329      379000.292
     1946902.141      379092.739     1946928.183      379323.208
#Sta/Elev= 30
       0 2026.73     9.8 2025.38    39.3  2019.8    49.1 2017.73    58.9 2015.38
    68.7  2013.2    78.6 2011.56    88.4 2010.38   117.8 2007.27   127.7 2005.42
   147.3 1996.01   157.1 1993.23     167 1991.65   176.8 1990.64   186.6  1989.8
   224.8 1986.87   241.7 1985.39   252.6 1984.74   261.7  1984.9   271.2 1986.31
   280.4  1988.4   289.7 1989.82   337.7 1993.48     386 1997.58   424.6 2002.08
   453.6 2004.91   463.3 2005.71   482.6  2007.1     502 2008.25   530.9 2010.13
#Mann= 3 , 0 , 0
       0      .1       0   241.7    .045       0   261.7      .1       0
Bank Sta=241.7,261.7
XS Rating Curve= 0 ,0
Exp/Cntr=0.3,0.1

Type RM Length L Ch R = 1 ,6991.7  ,457.1,462.4,467.6
XS GIS Cut Line= 4
     1946516.724      378758.104     1946498.495      378876.594
     1946510.214      378956.021     1946580.526      379203.417
#Sta/Elev= 30
       0 2020.13    18.4 2016.95    55.3 2010.98    64.6 2009.14      83 2004.41
   101.4 1999.79   110.7 1997.12   119.9 1993.04   128.8 1986.52   137.7 1977.83
   146.6 1970.49   149.8 1969.25   155.6 1966.99   164.5 1966.86   169.8 1968.03
   173.4 1968.82   182.3 1971.77   191.2 1974.57   200.2  1976.5   209.7 1977.46
   219.2 1977.56   228.8 1977.81   257.3 1980.15   266.8 1981.15   285.9 1984.02
   295.4 1985.02   333.5 1987.28   352.6 1988.52   371.6 1989.45   457.4  1991.9
#Mann= 3 , 0 , 0
       0      .1       0   149.8    .045       0   169.8      .1       0
Bank Sta=149.8,169.8
XS Rating Curve= 0 ,0
Exp/Cntr=0.3,0.1

Type RM Length L Ch R = 1 ,6529.3  ,454.4,452.5,449.9
XS GIS Cut Line= 4
     1946207.697      378873.121      1946112.21      379055.413
       1946105.7      379155.239     1946129.572      379370.083
#Sta/Elev= 30
       0  1973.4    39.2 1970.02      98 1962.52   166.6 1955.13   176.4 1954.42
   214.9 1952.58     224 1951.84   233.1  1950.8   242.2  1949.5   259.1 1946.79
   260.4 1946.59   269.4  1946.3   278.5  1948.4   287.6 1953.09   296.7 1958.96
   305.8 1964.11   315.6 1967.76   325.5 1969.38   335.3 1970.08   345.1 1971.03
   384.4 1976.82   413.9 1980.68   423.7 1981.61   433.6  1982.3   453.2 1983.31
   472.9 1984.81   482.7 1985.84   492.5 1987.19   512.2 1990.29     522 1991.35
#Mann= 3 , 0 , 0
       0      .1       0   259.1    .045       0   278.5      .1       0
Bank Sta=259.1,278.5
XS Rating Curve= 0 ,0
Exp/Cntr=0.3,0.1

Type RM Length L Ch R = 1 ,6076.8  ,640.4,630.2,619.4
XS GIS Cut Line= 4
     1945808.391       378701.68     1945749.797      378834.059
     1945751.967      378929.545     1945801.881      379196.472
#Sta/Elev= 30
       0 1954.13    19.3 1952.44    86.9 1947.19    96.5 1946.59   106.2  1946.5
   115.8 1946.03   135.1 1942.84   144.8 1941.73   154.3 1940.24   163.9 1936.71
   173.4 1932.32     179 1930.76     183 1929.64   192.5 1929.66     199 1930.51
   211.6 1932.04   221.2 1932.86   230.7 1933.45     250 1934.11   288.8 1934.25
   298.5 1934.76   308.2 1936.52   317.9 1939.16   337.3 1944.17     347 1946.34
   356.7 1947.76   395.4 1951.02   453.6 1954.14   492.4 1956.35   511.8  1957.6
#Mann= 3 , 0 , 0
       0      .1       0     179    .045       0     199      .1       0
Bank Sta=179,199
XS Rating Curve= 0 ,0
Exp/Cntr=0.3,0.1

Type RM Length L Ch R = 1 ,5446.6  ,535.3,533.6,531
XS GIS Cut Line= 4
     1945240.267       378603.12     1945307.541      378822.304
     1945359.624      378948.172     1945505.024      379288.884
#Sta/Elev= 30
       0 1931.49    28.7 1933.61    66.9 1933.96      86 1933.32    95.5 1932.32
   124.2  1927.9   133.7 1926.88   143.3  1926.2   191.1 1924.24   200.6 1923.58
   210.2 1922.49   229.3 1919.66     239 1917.84   248.7 1915.57   270.3 1909.66
   277.9 1908.27   287.7 1908.64   290.3 1909.19   297.4 1910.69   307.1  1913.4
   326.6  1917.4     346 1920.46   365.5 1922.87     385 1924.48     424 1925.98
   492.2 1930.24   511.7 1931.14   599.5 1937.66   687.2 1944.54   735.9  1951.3
#Mann= 3 , 0 , 0
       0      .1       0   270.3    .045       0   290.3      .1       0
Bank Sta=270.3,290.3
XS Rating Curve= 0 ,0
Exp/Cntr=0.3,0.1

Type RM Length L Ch R = 1 ,4913    ,483.6,471,458.3
XS GIS Cut Line= 4
     1944730.284       378768.05      1944825.77      378935.151
     1944888.704      379058.849     1945075.336      379291.054
#Sta/Elev= 30
       0 1949.87     9.6 1947.77    48.1 1938.48   115.5 1923.88   134.7 1919.34
   144.3 1917.43   173.2 1912.35   182.8  1910.5   192.5 1908.36   201.7  1904.8
     211 1900.24   220.2 1897.24   229.5  1896.5   231.7 1896.59   238.7 1896.86
   251.7 1896.57   266.5  1896.3     285 1896.24   340.9 1896.89   360.1 1897.52
   369.7  1898.1   408.1 1901.01     437 1902.69   494.6 1905.66   523.4 1906.73
   590.7 1908.23   600.3 1908.92   609.9 1910.22   619.6 1911.31   629.2 1911.87
#Mann= 3 , 0 , 0
       0      .1       0   231.7    .045       0   251.7      .1       0
Bank Sta=231.7,251.7
XS Rating Curve= 0 ,0
Exp/Cntr=0.3,0.1

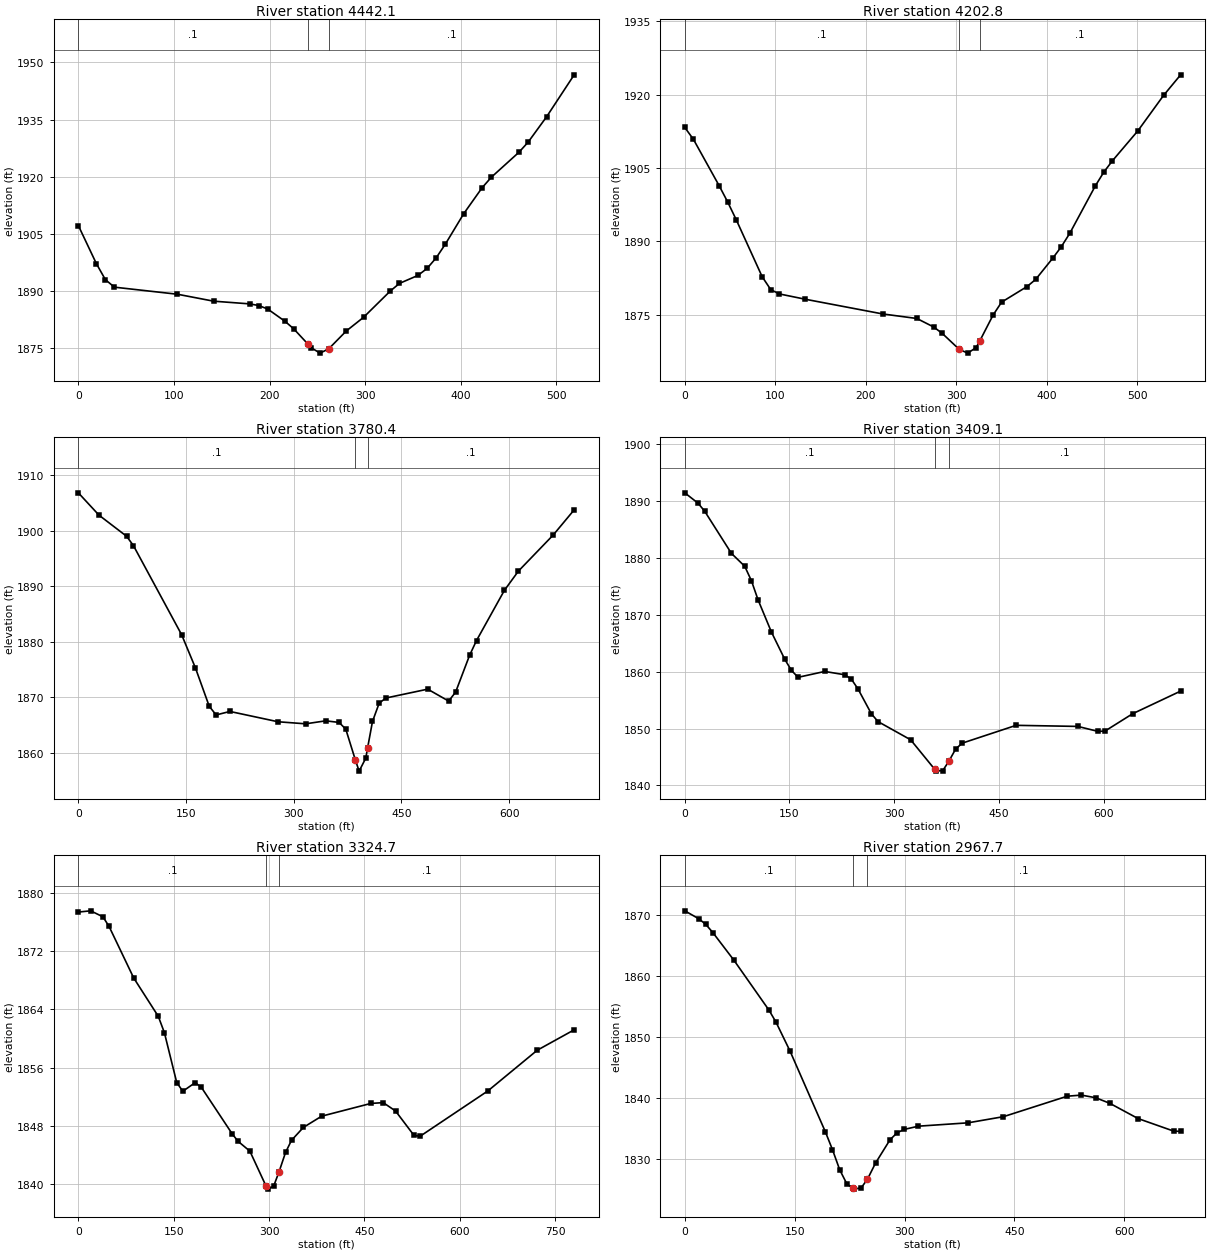
Type RM Length L Ch R = 1 ,4442.1  ,232.9,239.3,245.2
XS GIS Cut Line= 4
     1944537.142      379267.182     1944699.902       379380.03
     1944797.558      379447.304      1944975.51       379542.79
#Sta/Elev= 30
       0 1907.17    18.9 1897.15    28.3 1892.96    37.7 1890.99   103.7 1889.13
   141.5 1887.31   179.2  1886.6   188.6 1886.17     198 1885.26   216.3    1882
   225.4 1880.02   239.7 1876.16   243.7 1875.06   252.8 1873.67   261.9  1874.8
   280.2 1879.47   298.4 1883.09   326.3 1889.98   335.9 1891.98   355.1 1894.06
   364.7 1895.89   374.3 1898.69     384 1902.34   403.2 1910.32   422.4 1917.12
     432 1919.86   460.9 1926.42   470.5 1929.08   489.7  1935.7   518.6 1946.74
#Mann= 3 , 0 , 0
       0      .1       0   239.7    .045       0   261.9      .1       0
Bank Sta=239.7,261.9
XS Rating Curve= 0 ,0
Exp/Cntr=0.3,0.1

Type RM Length L Ch R = 1 ,4202.8  ,412.9,422.3,430.6
XS GIS Cut Line= 4
     1944424.295       379393.05     1944600.076      379566.662
      1944673.86      379651.297     1944845.301      379729.422
#Sta/Elev= 30
       0 1913.31     9.5 1910.89      38 1901.39    47.5 1898.03      57 1894.38
    85.5 1882.79      95 1880.15   104.5 1879.28     133  1878.2   218.6 1875.19
   256.4 1874.26   275.1 1872.51   284.5  1871.2   303.2 1867.95   312.6 1867.18
   321.9 1868.32   325.7  1869.6   340.6 1874.96     350  1877.6   378.2  1880.8
   387.6 1882.24   406.4 1886.56   415.9 1888.91   425.3 1891.66   453.6 1901.38
     463  1904.2   472.4 1906.49   500.6 1912.63   528.9 1919.85   547.8 1924.07
#Mann= 3 , 0 , 0
       0      .1       0   303.2    .045       0   325.7      .1       0
Bank Sta=303.2,325.7
XS Rating Curve= 0 ,0
Exp/Cntr=0.3,0.1

Type RM Length L Ch R = 1 ,3780.4  ,358.2,371.4,384.5
XS GIS Cut Line= 4
     1944260.666       379427.61     1944272.385      379744.016
     1944312.749      379848.183     1944453.374      380069.537
#Sta/Elev= 30
       0 1906.83    28.8  1902.8    67.2    1899    76.8  1897.3   143.9 1881.24
   163.1 1875.26   182.3 1868.35   191.9 1866.78   211.1 1867.41   278.2 1865.55
   316.6 1865.18   344.6 1865.72   363.2 1865.43   372.5 1864.22   385.8 1858.68
   391.1 1856.65   400.4    1859  402.87 1860.82   409.7  1865.6     419  1868.9
   428.3 1869.83   486.6 1871.43   515.8 1869.28   525.5  1870.9   544.9 1877.52
   554.6  1880.2   593.5 1889.26   612.9 1892.71   661.4 1899.22   690.6 1903.76
#Mann= 3 , 0 , 0
       0      .1       0   385.8    .045       0  402.87      .1       0
Bank Sta=385.8,402.87
XS Rating Curve= 0 ,0
Exp/Cntr=0.3,0.1

Type RM Length L Ch R = 1 ,3409.1  ,83.9,84.4,84.9
XS GIS Cut Line= 4
     1944034.104      379525.266     1943965.093      379813.027
     1943946.864      379931.516     1943985.492      380223.617
#Sta/Elev= 30
       0 1891.38    19.1 1889.55    28.6 1888.13    66.8 1880.75    85.9 1878.48
    95.5 1875.93     105 1872.58   124.1 1866.94   143.2 1862.16   152.7 1860.22
   162.3 1858.99   200.5 1860.02   229.1 1859.44   238.6 1858.68   248.2 1856.94
   267.3 1852.59   276.8 1851.22   323.6 1848.02   358.2 1842.82   360.5 1842.52
   369.7 1842.63   378.2 1844.23   388.1  1846.4   397.4 1847.43   474.7 1850.56
   563.1 1850.37   592.6 1849.48   602.4 1849.58   641.7  1852.6   710.4 1856.57
#Mann= 3 , 0 , 0
       0      .1       0   358.2    .045       0   378.2      .1       0
Bank Sta=358.2,378.2
XS Rating Curve= 0 ,0
Exp/Cntr=0.3,0.1

Type RM Length L Ch R = 1 ,3324.7  ,333.9,357.1,379.8
XS GIS Cut Line= 4
     1943914.312      379572.575     1943881.326      379812.159
     1943860.492       379931.95     1943858.756      380348.617
#Sta/Elev= 30
       0 1877.33    19.4  1877.5    38.7 1876.68    48.4 1875.35    87.1 1868.29
   125.8 1863.02   135.4 1860.78   154.8 1853.94   164.4 1852.74   183.8 1853.92
   193.5 1853.29   241.8 1846.93   251.2 1845.88   269.9 1844.52   295.6 1839.68
     298 1839.31   307.3 1839.72   315.6 1841.64     326 1844.34   335.4 1846.01
   354.1 1847.78   382.8 1849.32   460.3 1851.07   479.7 1851.18   499.1 1850.03
   528.2 1846.67   537.8 1846.57   644.4 1852.79     722 1858.37   780.1 1861.17
#Mann= 3 , 0 , 0
       0      .1       0   295.6    .045       0   315.6      .1       0
Bank Sta=295.6,315.6
XS Rating Curve= 0 ,0
Exp/Cntr=0.3,0.1

Type RM Length L Ch R = 1 ,2967.7  ,196,187,178.1
XS GIS Cut Line= 4
     1943834.451      379537.853     1943681.673      379636.811
     1943586.187      379687.159     1943398.687        380025.7
#Sta/Elev= 30
       0 1870.71    19.2  1869.4    28.7 1868.48    38.3 1867.14    67.1  1862.6
     115  1854.4   124.5 1852.45   143.7 1847.69   191.8 1834.48   201.6 1831.53
   211.5 1828.22   221.3 1825.89   229.4 1825.19   231.1 1825.04   240.9 1825.26
   249.4 1826.67   260.5 1829.33   280.2 1833.14     290  1834.3   299.6 1834.84
     319 1835.37   386.7 1835.92   435.1 1836.93   522.2 1840.29   541.5 1840.47
   560.9 1840.04   580.2 1839.13   618.9 1836.62   667.3 1834.57     677 1834.51
#Mann= 3 , 0 , 0
       0      .1       0   229.4    .045       0   249.4      .1       0
Bank Sta=229.4,249.4
XS Rating Curve= 0 ,0
Exp/Cntr=0.3,0.1

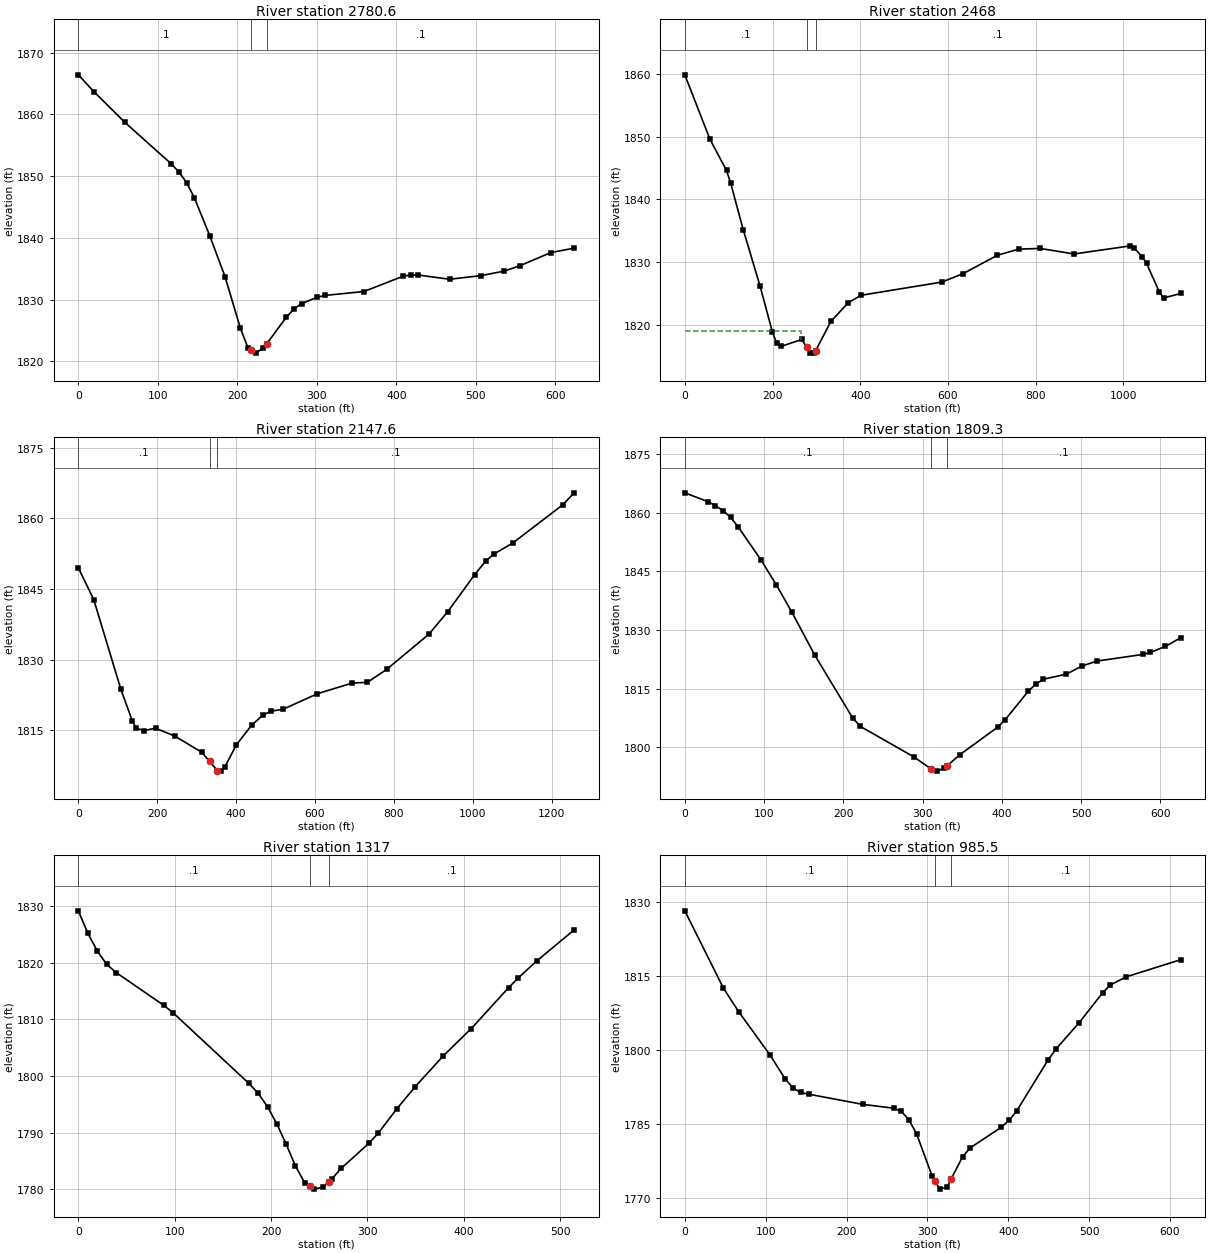
Type RM Length L Ch R = 1 ,2780.6  ,318.8,312.7,306.3
XS GIS Cut Line= 4
     1943723.904      379328.189     1943599.121      379450.801
     1943535.102      379522.416     1943389.702      379843.597
#Sta/Elev= 30
       0  1866.4    19.4  1863.7    58.3 1858.73   116.6 1852.02   126.4  1850.7
   136.1 1848.96   145.8 1846.54   165.2 1840.38   184.6 1833.69   203.8 1825.39
   213.4  1822.2   217.1 1821.87     223 1821.35   232.6 1822.17   237.1 1822.89
   261.4 1827.13     271 1828.48   280.8 1829.38   300.4 1830.39   310.2 1830.69
   359.1 1831.32   408.1 1833.78   417.9 1833.99   427.7 1833.99   466.9 1833.31
     506 1833.89   535.4 1834.62     555 1835.48   594.2 1837.62   623.6 1838.35
#Mann= 3 , 0 , 0
       0      .1       0   217.1    .045       0   237.1      .1       0
Bank Sta=217.1,237.1
XS Rating Curve= 0 ,0
Exp/Cntr=0.3,0.1

Type RM Length L Ch R = 1 ,2468    ,268.9,320.3,361.1
XS GIS Cut Line= 5
     1943587.185      379073.197     1943401.584      379189.119
      1943344.13      379298.892     1943258.572      379638.989
     1943050.239      380023.103
#Sta/Elev= 30
       0 1859.82    57.1  1849.6    95.1  1844.6   104.7 1842.56   133.2 1835.17
   171.3 1826.27   199.8 1818.86   209.3 1817.16   218.8 1816.59   266.5  1817.7
   278.1 1816.47   285.5 1815.54   295.1 1815.53   298.1 1815.89   333.2 1820.59
     372  1823.5   401.2 1824.73   586.3 1826.84     635  1828.2   712.8 1831.11
   761.4 1832.08     810 1832.19   887.6 1831.31  1013.9 1832.58  1023.6 1832.33
    1043 1830.85  1052.7  1829.8  1081.8 1825.29  1091.6 1824.31  1130.4 1825.02
#Mann= 3 , 0 , 0
       0      .1       0   278.1    .045       0   298.1      .1       0
#XS Ineff= 2 , 0
          265.84 1819.01
Permanent Ineff=
       F       F
Bank Sta=278.1,298.1
XS Rating Curve= 0 ,0
Exp/Cntr=0.3,0.1

Type RM Length L Ch R = 1 ,2147.6  ,348.4,338.3,328.2
XS GIS Cut Line= 5
     1943529.676       379068.64     1943356.499      379159.786
     1943152.072      379067.338     1942848.196      379141.124
     1942328.016      379203.659
#Sta/Elev= 30
       0 1849.49    39.1 1842.75   107.6 1823.76     137 1816.94   146.8 1815.44
   166.3 1814.94   195.7 1815.44   244.5 1813.77   312.8 1810.34   332.7 1808.38
   352.7 1806.43   361.5 1806.33   371.3  1807.2   400.6 1811.92   439.6 1816.11
   468.9 1818.29   488.5 1819.07   517.8 1819.42   605.7 1822.76   693.7 1825.02
   732.8  1825.2   781.3 1827.92     888 1835.36   936.5  1840.2  1004.4 1848.04
  1033.5 1851.02  1052.9  1852.4  1101.4 1854.78  1227.6 1862.86  1256.7 1865.42
#Mann= 3 , 0 , 0
       0      .1       0   332.7    .045       0   352.7      .1       0
Bank Sta=332.7,352.7
XS Rating Curve= 0 ,0
Exp/Cntr=0.3,0.1

Type RM Length L Ch R = 1 ,1809.3  ,506.3,492.3,477.7
XS GIS Cut Line= 3
     1943597.819      378789.994     1943347.819      378772.633
     1942972.819      378763.953
#Sta/Elev= 30
       0 1865.11    28.9 1862.88    38.6 1861.84    48.2 1860.56    57.8 1858.82
    67.5 1856.34    96.4 1847.87   115.7  1841.5   134.9 1834.65   163.9 1823.61
     212 1807.44   221.7 1805.32   289.1 1797.53   310.8 1794.44   317.9 1793.89
   327.6 1794.64   330.8  1795.2   346.8 1798.05   394.9 1805.15   404.5 1807.09
   433.3 1814.31     443 1816.16   452.6 1817.41   481.4  1818.7   500.7 1820.74
   519.9 1822.05   577.6 1823.74   587.2 1824.25   606.5  1825.8   625.7 1828.03
#Mann= 3 , 0 , 0
       0      .1       0   310.8    .045       0   330.8      .1       0
Bank Sta=310.8,330.8
XS Rating Curve= 0 ,0
Exp/Cntr=0.3,0.1

Type RM Length L Ch R = 1 ,1317    ,335.2,331.6,328.1
XS GIS Cut Line= 4
     1943438.097      378171.939     1943266.222      378267.425
     1943160.319      378331.661      1942998.86        378439.3
#Sta/Elev= 30
       0  1829.2     9.8 1825.25    19.7 1822.08    29.5 1819.72    39.3 1818.28
    88.5 1812.51    98.3 1811.18     177 1798.68   186.8  1796.9   196.6 1794.48
   206.2 1791.44   215.7 1787.93   225.2 1784.11   234.7 1781.16     240 1780.51
   244.3 1779.99   253.8 1780.33     260 1781.32   263.3 1781.84   272.8 1783.68
   301.4 1788.07     311 1789.84   330.2 1794.13   349.6 1798.11   378.7 1803.56
   407.8 1808.39   446.6 1815.63   456.3 1817.31   475.7 1820.34   514.5 1825.84
#Mann= 3 , 0 , 0
       0      .1       0     240    .045       0     260      .1       0
Bank Sta=240,260
XS Rating Curve= 0 ,0
Exp/Cntr=0.3,0.1

Type RM Length L Ch R = 1 ,985.5   ,537.7,535.3,532.4
XS GIS Cut Line= 4
     1943293.999      377842.078      1943092.61      377987.911
     1942997.124      378066.036     1942816.569      378225.758
#Sta/Elev= 30
       0 1828.26    47.8 1812.54    66.9  1807.7   105.2 1799.02   124.3 1794.08
   133.9 1792.26   143.4 1791.36     153 1791.02     220 1788.95   258.1 1788.17
   267.6 1787.56   277.1 1785.81   286.6 1782.97   305.6 1774.48   309.2 1773.44
   315.1 1771.73   324.6 1772.16   329.2 1773.75   343.6 1778.34     353 1780.12
   391.3 1784.29     401 1785.71   410.6 1787.66   449.2 1797.98   458.8 1800.15
   487.7 1805.56   516.7 1811.62   526.3  1813.2   545.6 1814.84   613.1 1818.33
#Mann= 3 , 0 , 0
       0      .1       0   309.2    .045       0   329.2      .1       0
Bank Sta=309.2,329.2
XS Rating Curve= 0 ,0
Exp/Cntr=0.3,0.1

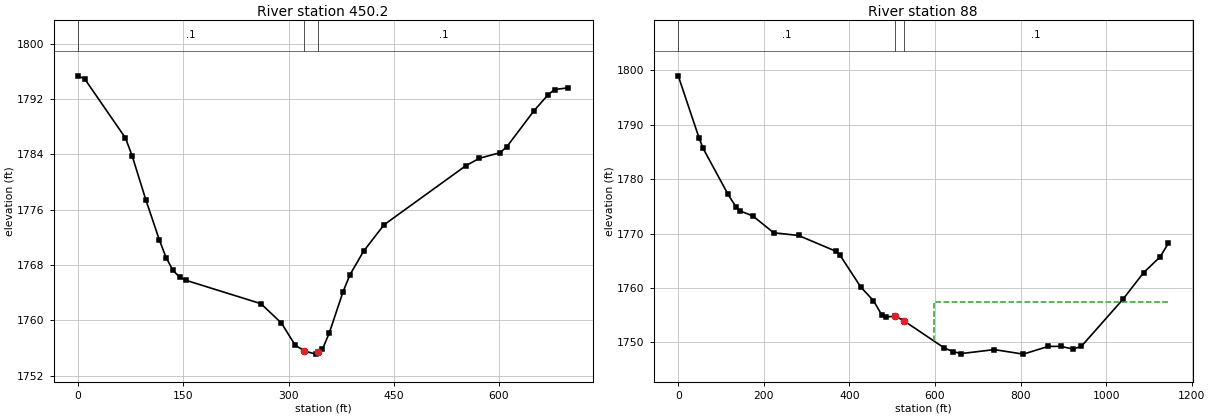
Type RM Length L Ch R = 1 ,450.2   ,365.8,362.2,358.2
XS GIS Cut Line= 4
     1942892.958      377451.453     1942698.513      377625.064
     1942590.874      377737.911     1942611.708      378019.161
#Sta/Elev= 30
       0 1795.38     9.6 1794.92    67.6 1786.38    77.2 1783.78    96.5 1777.48
   115.8 1771.66   125.5 1769.08   135.2 1767.25   144.8 1766.24   154.5 1765.77
   260.7 1762.41   289.9  1759.6   309.4 1756.42   322.6 1755.57   338.6 1755.11
   342.6 1755.41   348.4 1755.84   358.1 1758.17   377.6  1764.1   387.4 1766.56
   406.9 1769.99   436.1 1773.82   552.8 1782.38   572.2 1783.45   601.4 1784.26
   611.1 1785.11     650 1790.34   669.5 1792.59   679.2  1793.4   698.6 1793.64
#Mann= 3 , 0 , 0
       0      .1       0   322.6    .045       0   342.6      .1       0
Bank Sta=322.6,342.6
XS Rating Curve= 0 ,0
Exp/Cntr=0.3,0.1

Type RM Length L Ch R = 1 ,88      ,89.7,88,86.4
XS GIS Cut Line= 4
     1942792.408       377249.63     1942425.654      377375.498
     1942265.064      377596.852     1942280.255      378080.793
#Sta/Elev= 30
       0    1799    48.5 1787.62    58.2 1785.64   116.3 1777.22   135.7 1774.79
   145.4 1774.13   174.5 1773.22     223 1770.14   281.1 1769.64   368.4 1766.74
   378.1 1766.01   426.8 1760.13   456.1 1757.66   475.6 1755.03   485.4 1754.65
   507.3 1754.81   527.3 1753.95   622.2 1748.93   641.7  1748.3   661.2 1747.92
   738.7 1748.65   806.5 1747.82   864.6 1749.24   893.6 1749.25   922.7 1748.76
     942 1749.24  1038.9 1757.87  1087.3 1762.78    1126  1765.7  1145.4 1768.21
#Mann= 3 , 0 , 0
       0      .1       0   507.3    .045       0   527.3      .1       0
#XS Ineff= 2 , 0
                          596.86         1757.38
Permanent Ineff=
       F       F
Bank Sta=507.3,527.3
XS Rating Curve= 0 ,0
Exp/Cntr=0.3,0.1

Chan Stop Cuts=-1
Use User Specified Reach Order=0
Composite Channel Slope=5